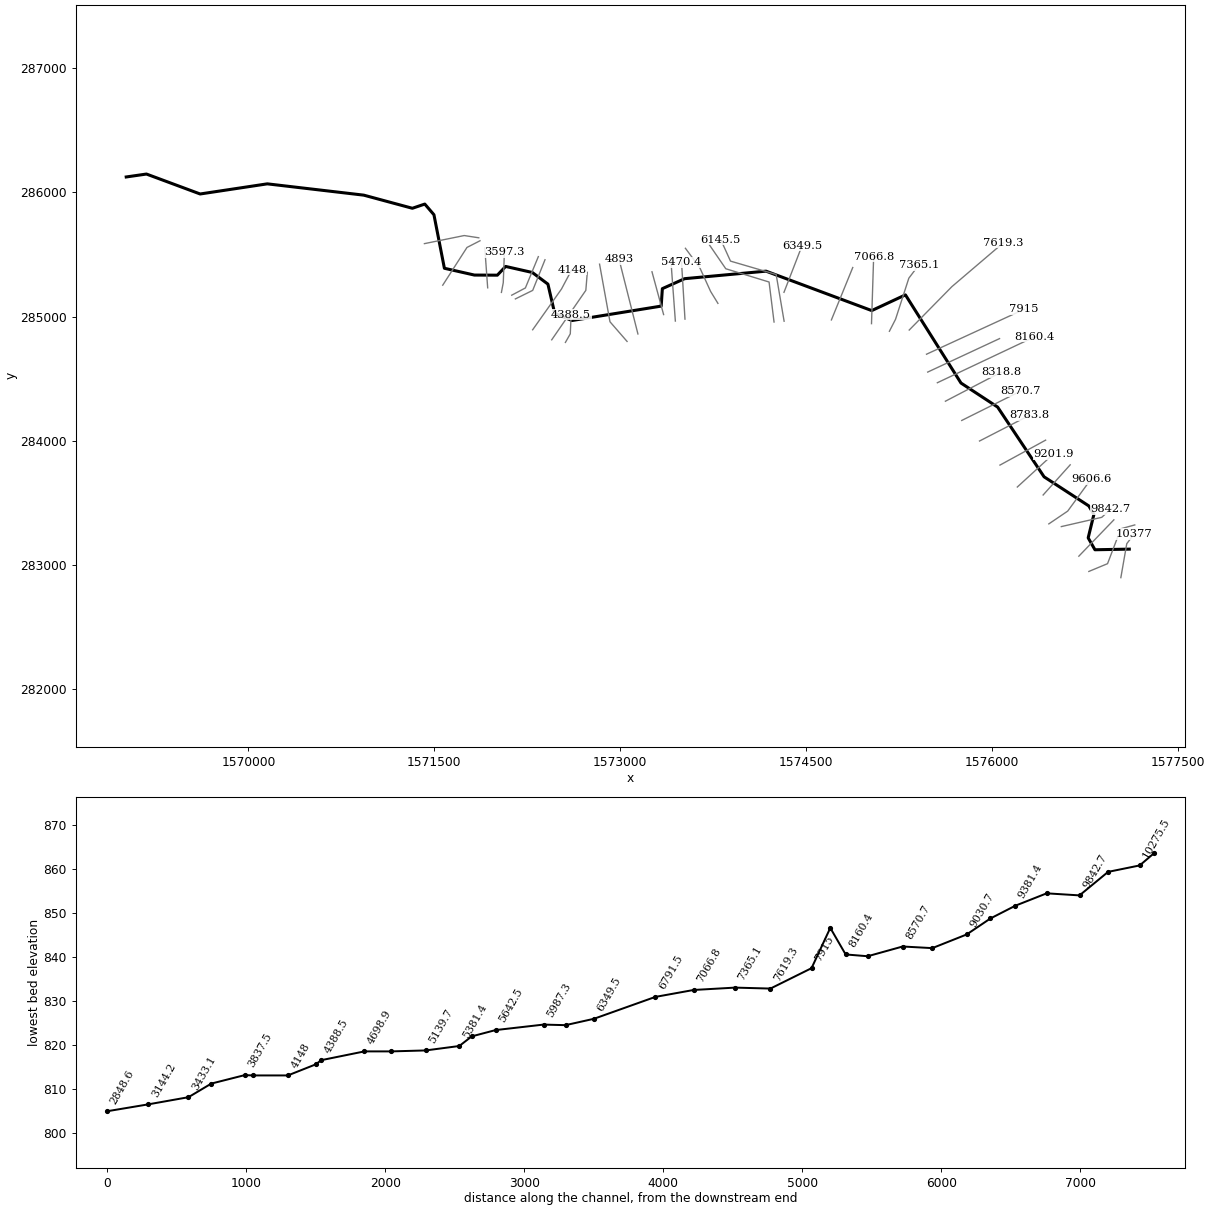
--- DOTSONRN.prj (project) ---

Proj Title=DOTSONRN
Current Plan=p01
Geom File=g01
Flow File=f01
Plan File=p01
DSS Export Rating Curves=0
DSS Export Rating Curve Sorted=0
DSS Export Volume Flow Curves=0
DXF OffsetX=0
DXF OffsetY=0
DXF ScaleX=0
DXF ScaleY=0

--- DOTSONRN.p01 (plan) ---

Plan Title=Floodplain
Program Version=4.00
Geom File=g01
Flow File=f01
K Sum by GR=0
Std Step Tol=0.01
Critical Tol=0.01
Num of Std Step Trials=20
Max Error Tol=0.3
Flow Tol Ratio=0.001
Split Flow NTrial=30
Split Flow Tol=0.02
Split Flow Ratio=0.02
Log Output Level=0
Friction Slope Method=1
Unsteady Friction Slope Method=2
Unsteady Bridges Friction Slope Method=1
Global Log Level=0
CheckData=False
Run HTab=0
Run UNet=0
Run PostProcess=0
UNET Theta=0
UNET Theta Warmup=0
UNET ZTol=0
UNET ZSATol=0
UNET MxIter=0
UNET MaxInSteps=0
UNET DtIC=0
UNET DtMin=0
UNET MaxCRTS=0
UNET WFStab=0
UNET SFStab=0
UNET WFX=0
UNET SFX=0
UNET DSS MLevel=0
UNET DZMax Abort=0
UNET Convert EG Bridges=0
UNET Use Existing IB Tables=0
UNET Froude Limit=0
UNET Froude Power=0
Write IC File=0
Echo Input=False
Echo Output=False
Write Detailed=0

--- DOTSONRN.f01 (steady flow) ---

Flow Title=NFF Regression Equation
Program Version=4.10
Number of Profiles= 1
Profile Names=P100yr
River Rch & RM=DOTSONRN,Main            ,10377
 494.501
River Rch & RM=DOTSONRN,Main            ,9201.9
 547.459
River Rch & RM=DOTSONRN,Main            ,7619.3
603.3262
River Rch & RM=DOTSONRN,Main            ,7365.1
876.0872
River Rch & RM=DOTSONRN,Main            ,6791.5
958.0906
River Rch & RM=DOTSONRN,Main            ,4698.9
1052.418
River Rch & RM=DOTSONRN,Main            ,4388.5
 1143.37
River Rch & RM=DOTSONRN,Main            ,2365.7
1178.215
River Rch & RM=DOTSONRN,Main            ,1926
1348.122
Boundary for River Rch & Prof#=DOTSONRN,Main            , 1
Up Type= 0
Dn Type= 1
Dn Known WS=801
DSS Import GetInterval= 0
DSS Import GetPeak= 0
DSS Import FillOption= 0

--- DOTSONRN.g01 (geometry) ---

Geom Title=USGS 10m DEM
Program Version=4.10

River Reach=DOTSONRN        ,Main
Reach XY= 30
     1577105.881      283127.401     1576828.848      283122.271
     1576774.126      283218.035     1576820.298      283406.828
     1576779.256      283475.231     1576418.429      283709.512
      1576043.58      284271.102     1575748.078      284464.683
     1575300.037      285174.366     1575028.134       285047.82
     1574175.514      285365.319     1573518.938      285304.733
      1573339.25      285224.524     1573329.876        285083.9
     1572609.563      284967.754     1572470.715      285026.002
      1572416.16      285260.896     1572290.292      285354.646
     1572075.014      285403.257     1572008.174      285332.945
     1571823.278      285333.813     1571581.091        285388.5
     1571496.745       285819.49      1571422.96      285905.427
     1571322.699      285871.573     1570930.708      285977.199
     1570152.435      286068.199     1569610.813      285986.609
     1569177.729      286147.124     1569014.475      286123.621

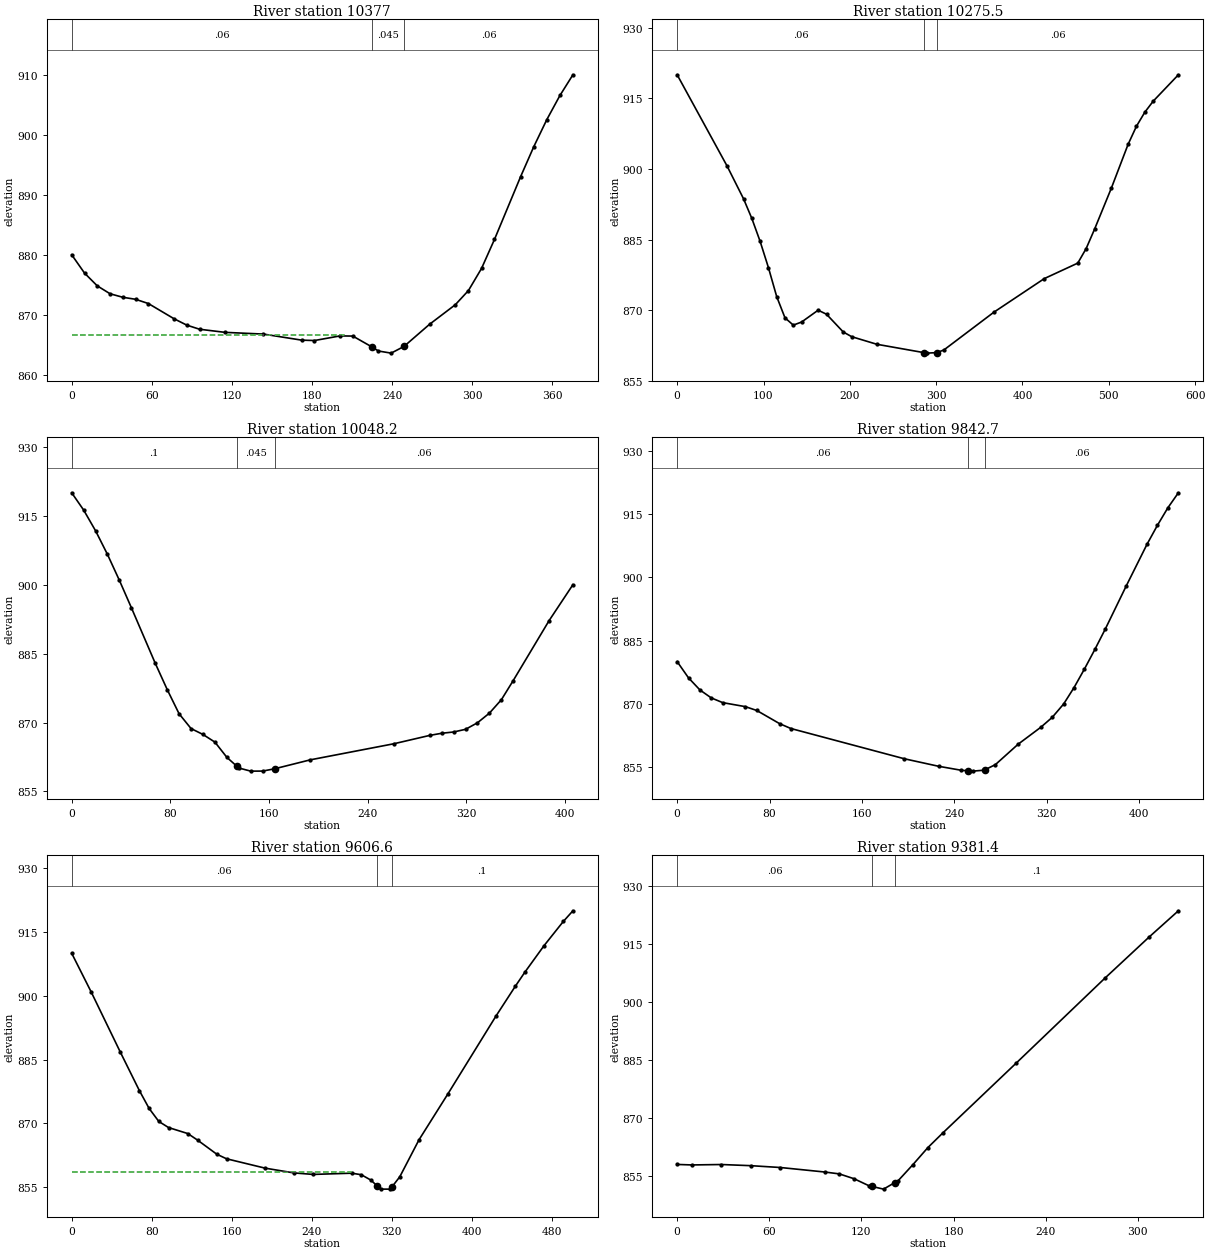
Type RM Length L Ch R = 1 ,10377   ,105.8,101.5,97.1
XS GIS Cut Line= 3
     1577037.671      282897.622     1577085.419      283171.009
      1577144.59      283248.893
#Sta/Elev= 30
       0  880.01     9.6  876.96    19.1  874.84    28.7  873.52    38.3  872.93
    47.8   872.6    57.4  871.89    76.6  869.36    86.1   868.3    95.7  867.61
   114.8  867.09   143.6   866.8   172.3  865.79   181.8  865.73     201   866.5
   210.5  866.47   224.5   864.7   229.7  863.98   239.2  863.63   248.8  864.74
     268  868.44   287.3   871.7   297.1  874.06   306.9  877.74   316.6  882.58
   336.2  893.05     346  898.01   355.8  902.54   365.6  906.55   375.3  909.99
#Mann= 3 , 0 , 0
       0     .06       0   224.5    .045       0   248.8     .06       0
#XS Ineff= 2 , 0
          205.07  866.68
Permanent Ineff=
       F       F
Bank Sta=224.5,248.8
XS Rating Curve= 0 ,0
Exp/Cntr=0.3,0.1

Type RM Length L Ch R = 1 ,10275.5 ,236.3,227.3,217.7
XS GIS Cut Line= 4
     1576779.567      282947.687     1576930.434      283010.299
     1577037.658      283291.307     1577150.016      283322.206
#Sta/Elev= 30
       0     920    57.6   900.7    76.9  893.66    86.5  889.49    96.1  884.62
   105.7  879.06   115.3  872.89   124.9  868.38   134.5  866.84   144.1  867.49
   163.3  870.01     173  869.15   192.4  865.38   202.2  864.38   231.3  862.77
   285.7     861   289.5  860.89   300.7     861   308.9  861.55   367.1  869.61
   425.3  876.72   464.1  880.01   473.8   883.1   483.5   887.2     503  895.94
   522.4  905.24   532.1  909.09   541.8  912.07   551.5  914.41   580.6     920
#Mann= 3 , 0 , 0
       0     .06       0   285.7    .045       0   300.7     .06       0
Bank Sta=285.7,300.7
XS Rating Curve= 0 ,0
Exp/Cntr=0.3,0.1

Type RM Length L Ch R = 1 ,10048.2 ,217.9,205.6,193
XS GIS Cut Line= 2
     1576698.936      283070.693     1576981.512      283363.111
#Sta/Elev= 30
       0  920.01     9.7  916.25    19.4  911.72      29   906.6    38.7  900.94
    48.4     895    67.8  882.88    77.5  877.16    87.1  871.91    96.8  868.69
   106.5   867.4   116.2  865.73   125.9  862.41   133.7  860.55   135.6   860.1
   145.2  859.42   154.9  859.43   164.6  859.93   193.6  861.88   261.4  865.38
   290.5   867.2   300.1  867.66   309.8  867.94   319.5  868.52   329.2  869.95
   338.9  872.05   348.6  874.97   358.2  879.14   387.3  892.19   406.6     900
#Mann= 3 , 0 , 0
       0      .1       0   133.7    .045       0   164.6     .06       0
Bank Sta=133.7,164.6
XS Rating Curve= 0 ,0
Exp/Cntr=0.3,0.1

Type RM Length L Ch R = 1 ,9842.7  ,220,236.1,252.1
XS GIS Cut Line= 3
      1576557.61      283308.802     1576883.757      283383.465
      1576956.73      283450.797
#Sta/Elev= 30
       0     880     9.8  876.16    19.7  873.29    29.5  871.41    39.4  870.29
      59  869.34    68.9  868.43    88.6  865.32    98.4  864.16   196.8  856.98
   226.3  855.21     246  854.26   251.8  854.14   255.9  854.06   265.7  854.28
   266.8  854.43   275.5   855.6   295.2  860.44   314.9  864.47   324.7   866.8
   334.6  869.97   343.6  873.86   352.6  878.25   361.7  882.93   370.7  887.75
   388.7  897.89   406.8  907.82   415.8  912.31   424.8  916.44   433.9     920
#Mann= 3 , 0 , 0
       0     .06       0   251.8    .045       0   266.8     .06       0
Bank Sta=251.8,266.8
XS Rating Curve= 0 ,0
Exp/Cntr=0.3,0.1

Type RM Length L Ch R = 1 ,9606.6  ,227.1,225.2,223.2
XS GIS Cut Line= 3
     1576456.845      283330.565     1576609.095      283433.602
     1576796.393      283689.797
#Sta/Elev= 30
       0     910    19.4  900.94    48.4  886.86    67.7  877.69    77.4  873.51
    87.1  870.45    96.8  869.02   116.1   867.6   125.8  866.07   145.1  862.74
   154.8  861.67   193.5  859.46   222.3  858.34   241.5  857.99     280  858.28
   289.6  857.92   299.2  856.65     305  855.38   308.9  854.53   318.5  854.53
     320  854.98   328.1  857.44   347.3  866.13   376.2  876.93   424.3  895.25
   443.5  902.21   453.1  905.54   472.4  911.82   491.6  917.49   501.2     920
#Mann= 3 , 0 , 0
       0     .06       0     305    .045       0     320      .1       0
#XS Ineff= 2 , 0
          279.72  858.58
Permanent Ineff=
       F       F
Bank Sta=305,320
XS Rating Curve= 0 ,0
Exp/Cntr=0.3,0.1

Type RM Length L Ch R = 1 ,9381.4  ,181.8,179.5,177.4
XS GIS Cut Line= 2
     1576410.877      283563.321      1576629.06      283806.053
#Sta/Elev= 20
       0  858.08     9.6  857.95    28.8  858.06      48  857.76    67.2  857.29
      96  856.13   105.6  855.64   115.2  854.39   124.8   852.6   126.7  852.42
   134.4  851.71   141.7  853.39     144  853.92   153.6  858.06   163.2   862.4
   172.8  866.13   220.8  884.23   278.4  906.08   307.2   916.7   326.4  923.52
#Mann= 3 , 0 , 0
       0     .06       0   126.7    .045       0   141.7      .1       0
Bank Sta=126.7,141.7
XS Rating Curve= 0 ,0
Exp/Cntr=0.3,0.1

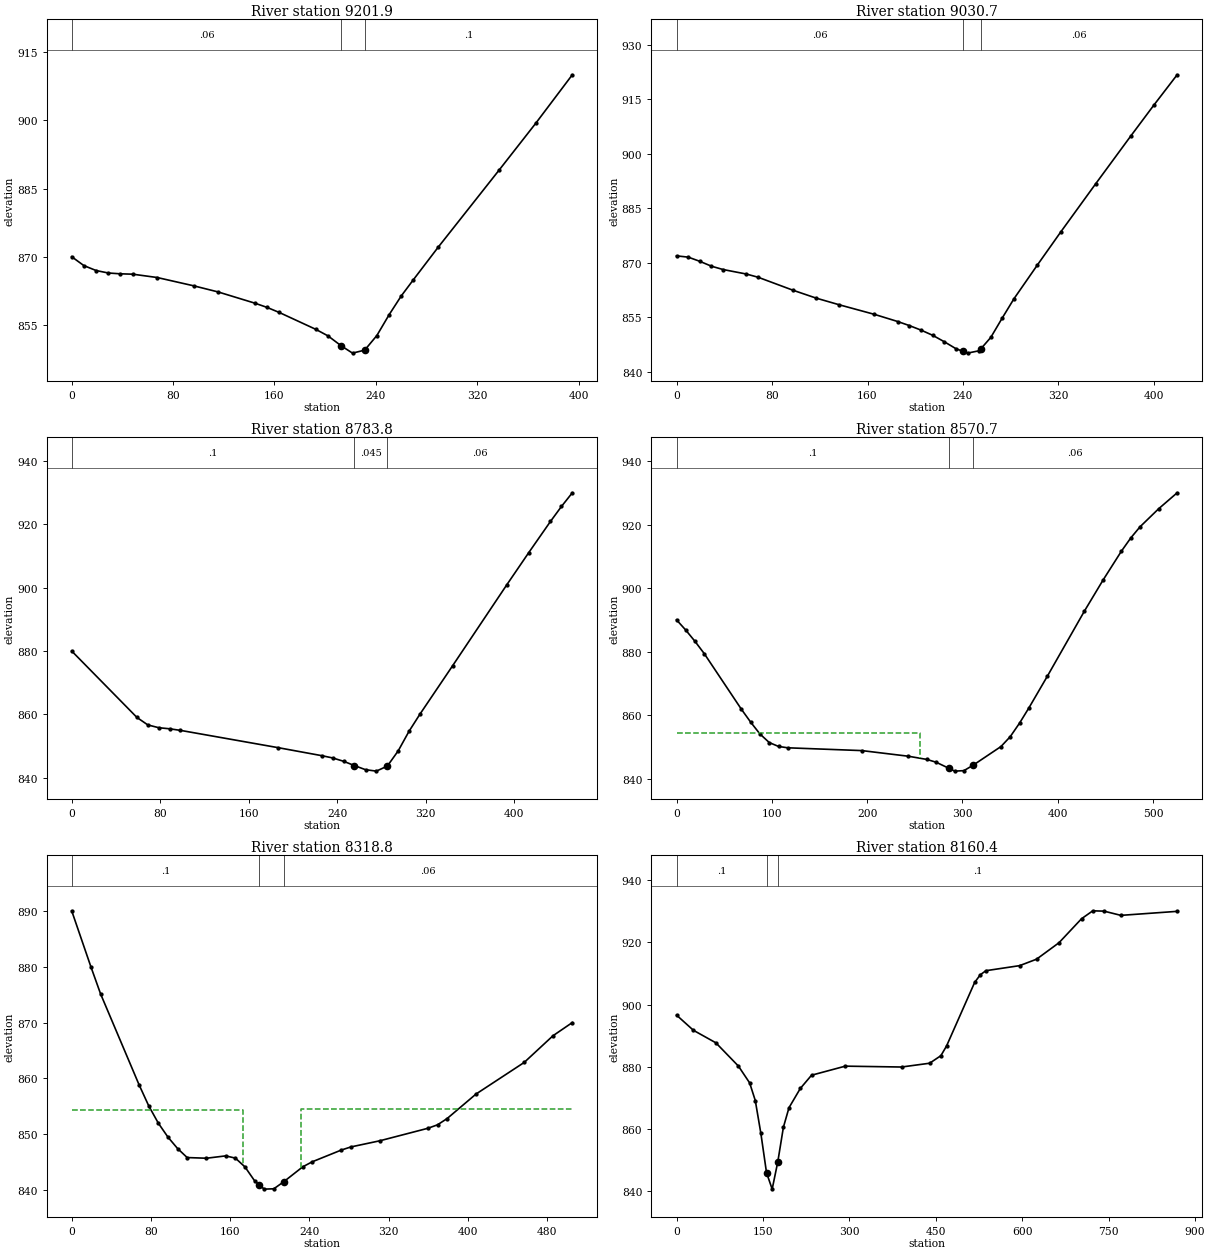
Type RM Length L Ch R = 1 ,9201.9  ,176.5,171.2,165.7
XS GIS Cut Line= 2
     1576202.517       283627.41     1576494.137      283893.778
#Sta/Elev= 25
       0     870     9.6  868.05    19.3  866.96    28.9  866.42    38.5  866.24
    48.2  866.16    67.4  865.43    96.3   863.6   115.6  862.25   144.5  859.79
   154.1  858.86   163.8  857.74   192.7  854.02   202.3  852.58   212.6  850.42
   221.6   848.8   231.2  849.46   240.8  852.67   250.5  857.26   260.1   861.4
   269.7  864.97     289  872.03   337.2  889.03   366.1  899.32     395     910
#Mann= 3 , 0 , 0
       0     .06       0   212.6    .045       0   231.2      .1       0
Bank Sta=212.6,231.2
XS Rating Curve= 0 ,0
Exp/Cntr=0.3,0.1

Type RM Length L Ch R = 1 ,9030.7  ,247.5,246.9,246.3
XS GIS Cut Line= 2
     1576062.624      283803.922     1576430.768      284004.745
#Sta/Elev= 30
       0  871.92     9.8  871.57    19.5  870.42    29.3  869.07      39  868.16
    58.5  866.92    68.3  866.04    97.5  862.47     117  860.29   136.5  858.44
   165.8  855.82   185.3  853.85     195  852.74   204.8  851.49   214.6  850.06
   224.3  848.29   234.1  846.37   240.2   845.6   243.8  845.15   253.6  845.81
   255.2  846.42   263.3  849.48   273.1  854.93   282.8  860.16   302.3  869.39
   321.8  878.45   351.1  891.73   380.4  904.83   399.8  913.36   419.4  921.75
#Mann= 3 , 0 , 0
       0     .06       0   240.2    .045       0   255.2     .06       0
Bank Sta=240.2,255.2
XS Rating Curve= 0 ,0
Exp/Cntr=0.3,0.1

Type RM Length L Ch R = 1 ,8783.8  ,213.8,213.1,212.3
XS GIS Cut Line= 2
     1575897.738       283997.77     1576300.073      284204.461
#Sta/Elev= 23
       0     880      59  858.99    68.8  856.64    78.7  855.76    88.5  855.42
    98.3  854.92   186.8  849.44   226.2  846.91     236  846.19   245.8  845.13
   255.5  843.79   265.5  842.49   275.3  842.04   285.2  843.64     295  848.44
   304.8  854.64   314.7  860.07   344.2  875.36   393.3  901.02     413  911.12
   432.6  920.96   442.5  925.68   452.3     930
#Mann= 3 , 0 , 0
       0      .1       0   255.5    .045       0   285.2     .06       0
Bank Sta=255.5,285.2
XS Rating Curve= 0 ,0
Exp/Cntr=0.3,0.1

Type RM Length L Ch R = 1 ,8570.7  ,251.2,251.9,252.6
XS GIS Cut Line= 2
     1575754.129      284163.262     1576224.333      284397.249
#Sta/Elev= 30
       0  890.01     9.7  886.79    19.4  883.24    29.2  879.34    68.1  861.86
    77.8  857.82    87.5  854.11    97.3   851.4     107  850.18   116.7  849.75
   194.5  848.87   243.2   847.1   262.6  846.09   272.3  845.22     286  843.27
   291.8  842.41   301.5  842.56   311.2  844.28   340.4  850.15   350.1  853.25
   359.9  857.52   369.6  862.26     389  872.25     428   892.8   447.4  902.49
   466.8  911.65   476.6   915.8   486.3   919.3   505.8  924.97   525.2  929.99
#Mann= 3 , 0 , 0
       0      .1       0     286    .045       0   311.2     .06       0
#XS Ineff= 2 , 0
          255.21  854.33
Permanent Ineff=
       F       F
Bank Sta=286,311.2
XS Rating Curve= 0 ,0
Exp/Cntr=0.3,0.1

Type RM Length L Ch R = 1 ,8318.8  ,159.2,158.4,157.6
XS GIS Cut Line= 2
      1575622.46      284318.273     1576070.914      284551.523
#Sta/Elev= 30
       0     890    19.4  879.98    29.2  875.12      68  858.88    77.8  855.09
    87.5  851.99    97.2   849.5   106.9  847.46   116.6  845.84   136.1  845.72
   155.5  846.14   165.3  845.74     175  844.16   184.7  841.68   189.5  840.94
   194.4  840.19   204.1  840.25   213.9  841.48   233.3  844.18     243  845.09
   272.2  847.18   281.9  847.74   311.1  848.84   359.7  851.08   369.4   851.7
   379.1  852.82   408.3  857.21   456.9  862.86     486  867.64   505.5     870
#Mann= 3 , 0 , 0
       0      .1       0   189.5    .045       0   213.9     .06       0
#XS Ineff= 2 , 0
          173.24  854.33  231.55          854.46
Permanent Ineff=
       F       F
Bank Sta=189.5,213.9
XS Rating Curve= 0 ,0
Exp/Cntr=0.3,0.1

Type RM Length L Ch R = 1 ,8160.4  ,110.5,110.4,110.3
XS GIS Cut Line= 2
     1575557.511      284466.985     1576343.346       284837.53
#Sta/Elev= 30
       0  896.61    29.3  891.72    68.3  887.69   107.4   880.2   126.9  874.79
   136.7  869.11   146.4  858.51   156.2  845.88     166   840.6   175.7  849.33
   185.5  860.53   195.2  866.81   214.8  872.99   234.3  877.26   292.9  880.18
   390.5   879.9   439.3  881.12   458.8  883.55   468.6  886.65   517.4  907.12
   527.2  909.58   536.9   910.9   595.5  912.53   624.8   914.6   663.8   919.9
   702.9  927.62   722.4  930.17   741.9  930.07   771.2  928.71   868.8     930
#Mann= 3 , 0 , 0
       0      .1       0   156.2    .045       0   175.7      .1       0
Bank Sta=156.2,175.7
XS Rating Curve= 0 ,0
Exp/Cntr=0.3,0.1

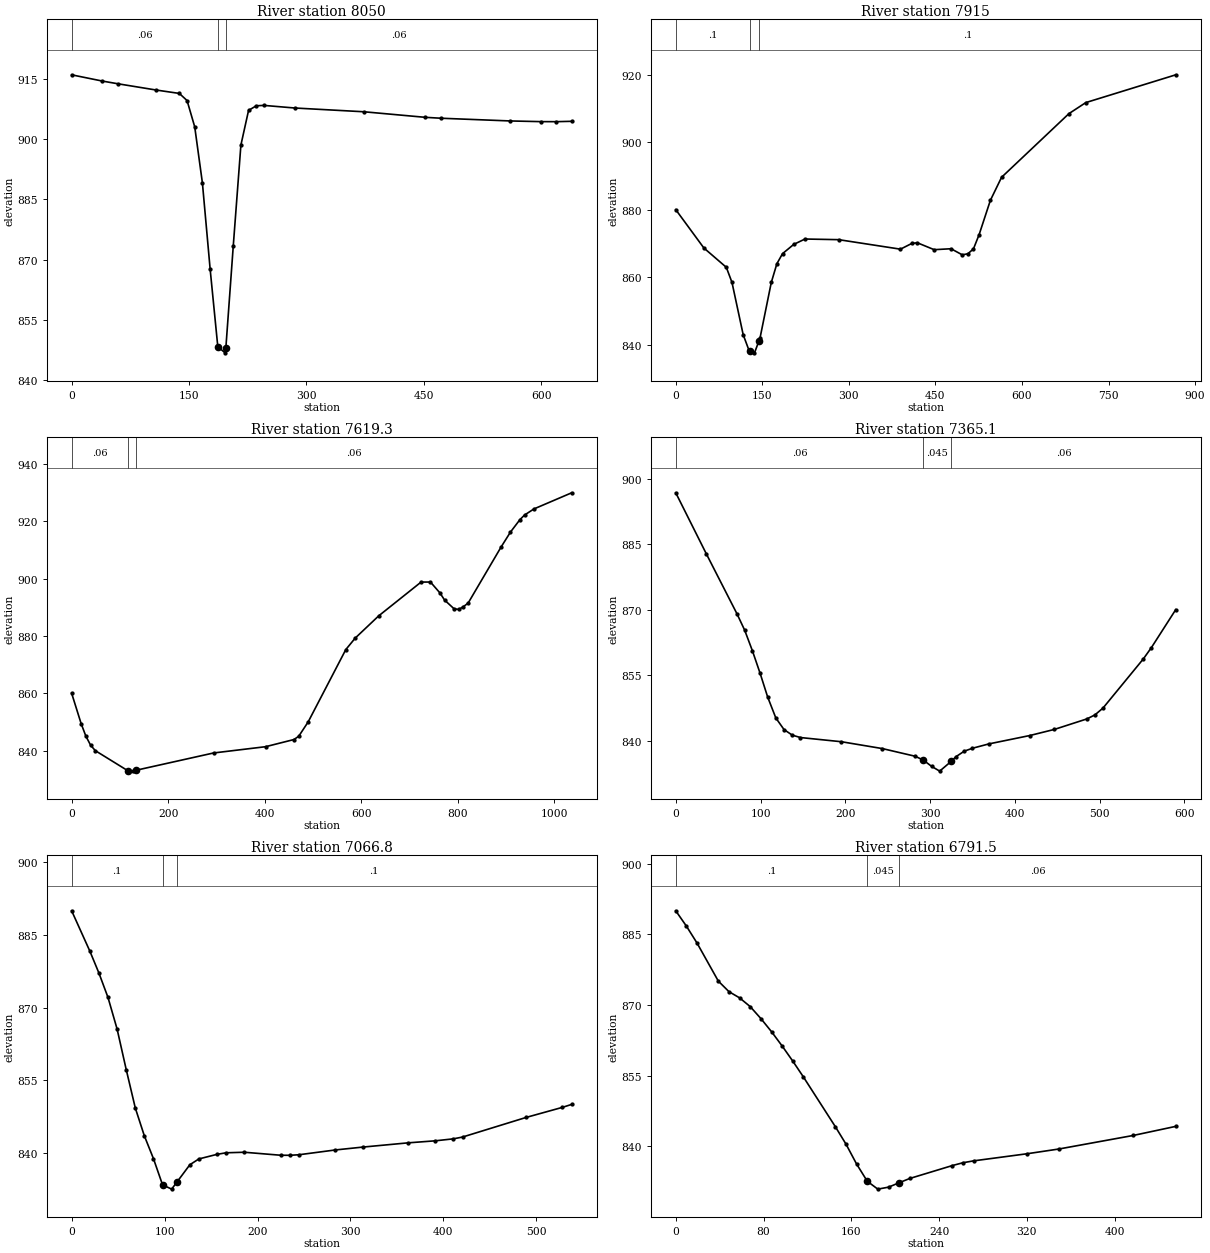
Type RM Length L Ch R = 1 ,8050    ,135.1,134.9,134.8
XS GIS Cut Line= 2
     1575479.681      284552.767     1576059.108      284822.298
#Sta/Elev= 25
       0   916.1    39.3  914.54      59  913.87   108.2   912.3   137.6  911.46
   147.5  909.68   157.3  903.11   167.1  889.14     177  867.61   186.8  848.24
   196.6  846.65  197.07847.9133   206.5  873.26   216.3  898.56   226.1  907.22
     236  908.38   245.8  908.47   285.1  907.82   373.6  906.88   452.2  905.49
   471.9  905.27   560.4  904.59   599.7  904.42   619.4  904.41     639   904.5
#Mann= 3 , 0 , 0
       0     .06       0   186.8    .045       0  197.07     .06       0
Bank Sta=186.8,197.07
XS Rating Curve= 0 ,0
Exp/Cntr=0.3,0.1

Type RM Length L Ch R = 1 ,7915    ,287.5,295.8,303.9
XS GIS Cut Line= 2
     1575470.143      284696.581     1576257.477      285058.169
#Sta/Elev= 30
       0     880    48.7  868.64    87.6  862.91    97.4  858.44   116.8  842.95
   126.6  838.42   129.2  838.17   136.3  837.47   144.2  841.11     146  841.94
   165.5  858.41   175.2  863.97     185  866.96   204.4   869.7   223.9   871.3
   282.3  871.11   389.4  868.29   408.9  869.98   418.6  870.19   447.8  868.14
     477  868.42   496.5  866.61   506.2  866.93   515.9  868.38   525.7   872.6
   545.2  882.76   564.6   889.6   681.4  908.48   710.6  911.75   866.4  919.98
#Mann= 3 , 0 , 0
       0      .1       0   129.2    .045       0   144.2      .1       0
Bank Sta=129.2,144.2
XS Rating Curve= 0 ,0
Exp/Cntr=0.3,0.1

Type RM Length L Ch R = 1 ,7619.3  ,243.3,254.1,265
XS GIS Cut Line= 3
     1575330.555      284891.249     1575674.655      285240.476
     1576090.599      285594.464
#Sta/Elev= 30
       0  859.99    19.6  849.43    29.4  845.05    39.2   841.9      49  839.97
   117.6  832.84   127.5  832.82   132.6  833.09   294.2  839.16     402  841.35
   460.8  843.85   470.7  844.99   490.3  850.01   568.3  875.26   587.8  879.27
   636.6  887.05   724.4  898.84   743.8  898.85   763.4  895.06   773.1  892.55
   792.6  889.53   802.4  889.27   812.1  890.25   821.9  891.49   890.2  911.07
   909.7   916.3   929.2  920.62   938.9  922.25   958.4  924.38  1036.4     930
#Mann= 3 , 0 , 0
       0     .06       0   117.6    .045       0   132.6     .06       0
Bank Sta=117.6,132.6
XS Rating Curve= 0 ,0
Exp/Cntr=0.3,0.1

Type RM Length L Ch R = 1 ,7365.1  ,291.9,298.3,304.7
XS GIS Cut Line= 4
     1575170.737      284881.429     1575220.278      284977.821
       1575327.5      285308.789     1575408.181      285415.076
#Sta/Elev= 30
       0  896.75    36.1  882.76    72.2  869.05    81.3  865.29    90.3  860.64
    99.4  855.48   108.4     850     118  845.22   127.7  842.55   137.4  841.28
     147  840.73   195.4  839.77   243.7   838.2   282.3  836.45     292  835.57
   301.7  834.14   311.3  833.04   324.9  835.28   330.6  836.36   340.3  837.61
     350  838.28   369.3  839.27   417.6  841.19   446.6  842.59   484.9  844.99
   494.4  845.91   503.9  847.47   551.6  858.75   561.1  861.34   589.7     870
#Mann= 3 , 0 , 0
       0     .06       0     292    .045       0   324.9     .06       0
Bank Sta=292,324.9
XS Rating Curve= 0 ,0
Exp/Cntr=0.3,0.1

Type RM Length L Ch R = 1 ,7066.8  ,283.4,275.4,267.1
XS GIS Cut Line= 2
     1575026.372      284942.641     1575043.655      285480.322
#Sta/Elev= 30
       0     890    19.6  881.66    29.3  877.16    39.1   872.1    48.9  865.57
    58.7  857.21    68.5  849.25    78.2  843.52      88  838.81    97.8  833.39
    98.2  833.35   107.6   832.5   113.2  833.94   127.2  837.54   136.9  838.74
   156.5  839.69   166.3  840.01   185.8  840.12     225   839.5   234.8  839.49
   244.5   839.6   283.6  840.59     313  841.18   361.9  842.06   391.2  842.48
   410.8  842.89   420.6  843.26     489  847.31   528.2   849.4     538     850
#Mann= 3 , 0 , 0
       0      .1       0    98.2    .045       0   113.2      .1       0
Bank Sta=98.2,113.2
XS Rating Curve= 0 ,0
Exp/Cntr=0.3,0.1

Type RM Length L Ch R = 1 ,6791.5  ,441.4,442,442.2
XS GIS Cut Line= 2
     1574702.821      284972.597     1574875.081      285394.562
#Sta/Elev= 27
       0     890     9.7  886.75    19.4  883.15    38.8  875.08    48.5  872.84
    58.2  871.52    67.9  869.66    77.6  867.13    87.3  864.34      97   861.3
   106.7  858.09   116.4  854.72   145.5  844.17   155.2  840.47   164.8  836.27
   174.6  832.59   184.2  830.92     194  831.34   203.6  832.27   213.3  833.18
   252.1  835.92   261.8  836.52   271.5  836.92     320  838.42   349.1  839.43
     417  842.31   455.8  844.24
#Mann= 3 , 0 , 0
       0      .1       0   174.6    .045       0   203.6     .06       0
Bank Sta=174.6,203.6
XS Rating Curve= 0 ,0
Exp/Cntr=0.3,0.1

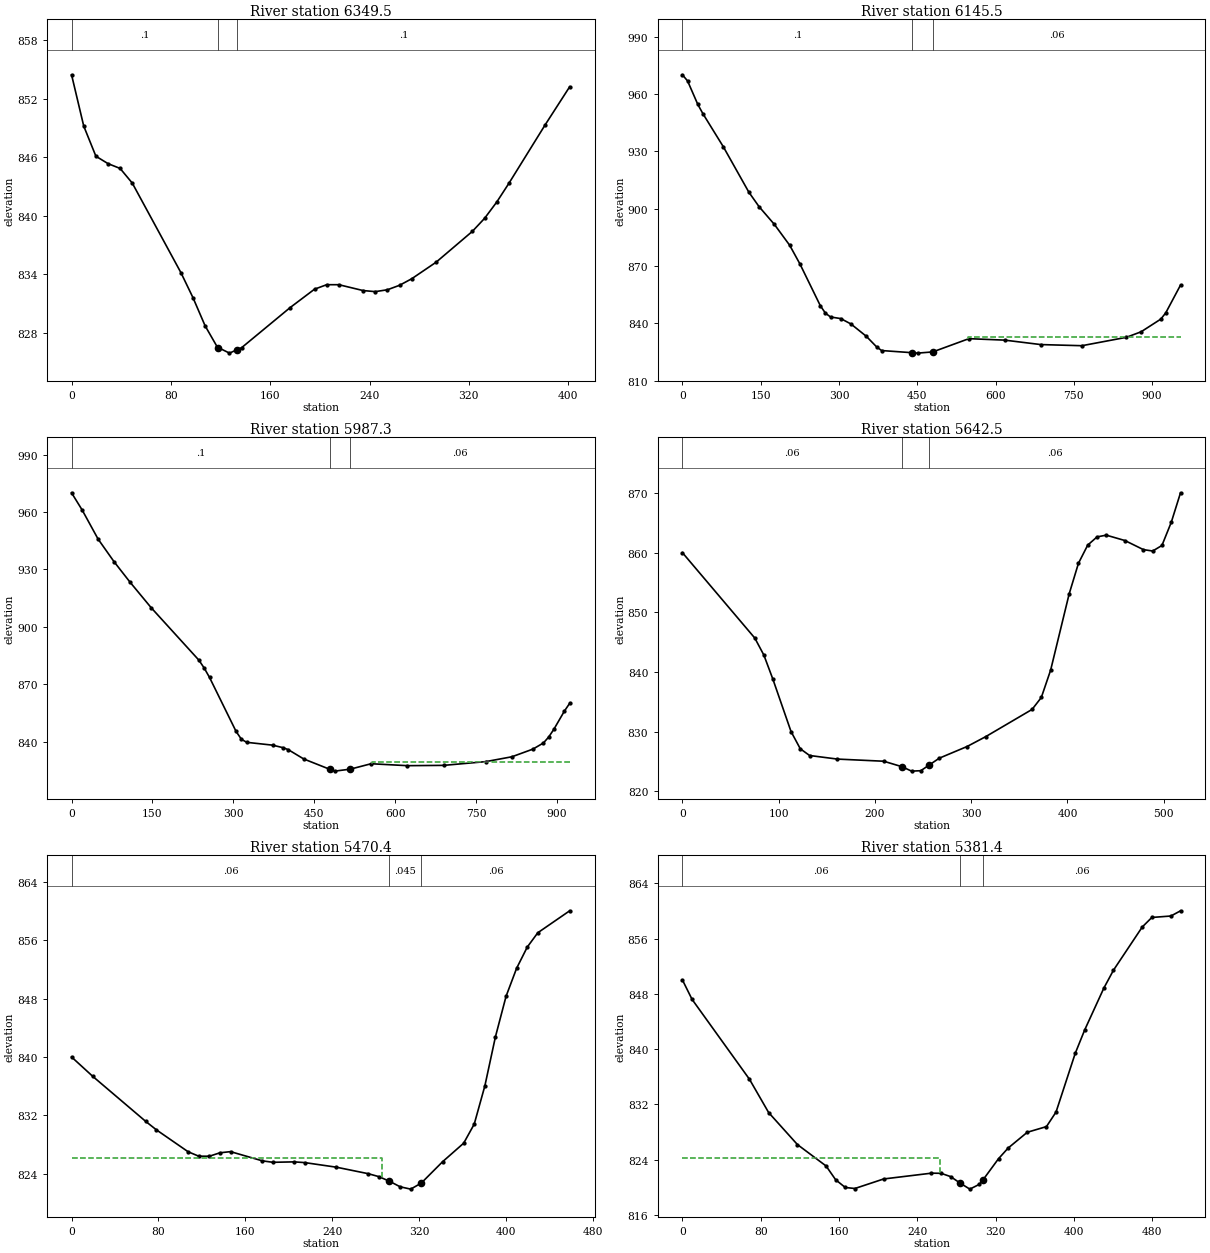
Type RM Length L Ch R = 1 ,6349.5  ,103,204,254.3
XS GIS Cut Line= 2
     1574320.342      285195.033     1574465.528      285569.044
#Sta/Elev= 30
       0  854.44     9.8  849.19    19.6   846.1    29.4  845.34    39.1  844.85
    48.9  843.35    88.1  834.17    97.8  831.61   107.6  828.72   117.4  826.55
   118.3  826.49   127.2  825.93   133.3  826.28     137  826.49   176.1   830.6
   195.7  832.48   205.5  832.94   215.3  832.94   234.8  832.34   244.6  832.23
   254.4  832.42   264.2  832.88     274  833.55   293.6  835.24   322.9  838.41
   332.7  839.74   342.5  841.41   352.3  843.33   381.6  849.34   401.2  853.21
#Mann= 3 , 0 , 0
       0      .1       0   118.3    .045       0   133.3      .1       0
Bank Sta=118.3,133.3
XS Rating Curve= 0 ,0
Exp/Cntr=0.3,0.1

Type RM Length L Ch R = 1 ,6145.5  ,198.3,158.3,173.8
XS GIS Cut Line= 4
      1574321.41      284962.325     1574257.258      285338.549
      1573888.92       285446.11      1573810.71      285618.219
#Sta/Elev= 30
       0     970     9.8  966.82    29.4  954.55    39.1  949.73    78.3   932.4
   127.2  908.66   146.8  901.07   176.2  891.78   205.5  880.87   225.1  871.12
   264.2  849.28     274  845.37   283.8  843.38   303.4  842.54   322.9  839.72
   352.3  833.29   371.9  827.79   381.6  825.83   440.7  824.69   450.5  824.48
   479.6  825.11   548.9  832.04   617.8  831.27   686.7  828.95   765.4  828.36
   850.4  832.73   878.8  835.62   916.6  842.26   926.1  845.53   954.4  860.04
#Mann= 3 , 0 , 0
       0      .1       0   440.7    .045       0   479.6     .06       0
#XS Ineff= 2 , 0
                          547.89             833
Permanent Ineff=
       F       F
Bank Sta=440.7,479.6
XS Rating Curve= 0 ,0
Exp/Cntr=0.3,0.1

Type RM Length L Ch R = 1 ,5987.3  ,386.6,344.7,296.6
XS GIS Cut Line= 4
     1574240.228      284955.766     1574200.037      285277.859
     1573850.885      285384.696     1573718.581      285577.095
#Sta/Elev= 30
       0     970    19.7  960.99    49.2  945.82    78.7  934.03   108.2  923.39
   147.5     910   236.1  882.55   245.9  878.43   255.7  873.56   304.9  845.36
   314.8  841.26   324.6  839.66   372.6  838.18   391.8  836.87   401.5  835.85
   430.3  830.97   478.3   825.6   487.9  824.61   516.8  825.65   555.2  828.47
   622.5  827.46   689.7  827.62   767.6  829.57   816.2  832.11   855.1  836.11
   874.6  839.32   884.3   842.4     894  846.48   913.5  855.98   923.2     860
#Mann= 3 , 0 , 0
       0      .1       0   478.3    .045       0   516.8     .06       0
#XS Ineff= 2 , 0
                          557.75          829.26
Permanent Ineff=
       F       F
Bank Sta=478.3,516.8
XS Rating Curve= 0 ,0
Exp/Cntr=0.3,0.1

Type RM Length L Ch R = 1 ,5642.5  ,180.7,172.1,163.1
XS GIS Cut Line= 4
     1573787.477      285105.976     1573728.423      285202.103
      1573640.46      285394.772      1573525.24      285549.363
#Sta/Elev= 30
       0     860    75.2  845.67    84.6  842.82      94  838.76   112.8     830
   122.4  827.11   132.1  825.98     161  825.38   209.1  825.02   228.3  824.09
     238  823.36   247.6  823.43     256  824.35   266.8  825.53   295.7  827.49
     315  829.14   363.2  833.71   372.8  835.71   382.5  840.31   401.7  853.07
   411.4  858.23     421  861.27   430.7  862.65   440.3  862.94   459.6  862.04
   478.9  860.51   488.5  860.28   498.1  861.21   507.8   865.1   517.4  870.04
#Mann= 3 , 0 , 0
       0     .06       0   228.3    .045       0     256     .06       0
Bank Sta=228.3,256
XS Rating Curve= 0 ,0
Exp/Cntr=0.3,0.1

Type RM Length L Ch R = 1 ,5470.4  ,88.4,89,88.3
XS GIS Cut Line= 2
     1573521.733      284979.031     1573494.036      285436.591
#Sta/Elev= 30
       0     840    19.5  837.35    68.3  831.18      78  830.04   107.3  827.03
     117  826.43   126.8  826.42   136.5  826.89   146.3  827.05   175.6  825.79
   185.3  825.59   204.8  825.65   214.6  825.55   243.8  824.92   273.1  824.03
   282.8  823.63   292.6     823   302.4  822.24   312.1  821.92   321.8  822.74
   341.4  825.66   360.9  828.21   370.6  830.82   380.4  836.06   390.1  842.76
   399.9  848.31   409.6  852.14   419.4  855.04   429.1     857   458.4     860
#Mann= 3 , 0 , 0
       0     .06       0   292.6    .045       0   321.8     .06       0
#XS Ineff= 2 , 0
          285.92  826.23
Permanent Ineff=
       F       F
Bank Sta=292.6,321.8
XS Rating Curve= 0 ,0
Exp/Cntr=0.3,0.1

Type RM Length L Ch R = 1 ,5381.4  ,235.2,241.7,246.6
XS GIS Cut Line= 2
      1573444.14      284963.472      1573406.64      285471.114
#Sta/Elev= 30
       0     850     9.8   847.2    68.5  835.63    88.1  830.81   117.5  826.18
   146.8  823.08   156.6  821.08   166.4  819.97   176.2  819.82   205.6   821.2
   254.5  822.04   264.3  822.02   274.1  821.54   283.9  820.59   293.7  819.73
   303.5  820.43     307  821.04     323  824.13   332.8  825.67   352.4  827.96
     372  828.78   381.8  830.89   401.4  839.38   411.1  842.78   430.7  848.84
   440.5  851.42   469.9  857.67   479.7  859.05   499.2  859.26     509  860.01
#Mann= 3 , 0 , 0
       0     .06       0   283.9    .045       0     307     .06       0
#XS Ineff= 2 , 0
          262.82   824.3
Permanent Ineff=
       F       F
Bank Sta=283.9,307
XS Rating Curve= 0 ,0
Exp/Cntr=0.3,0.1

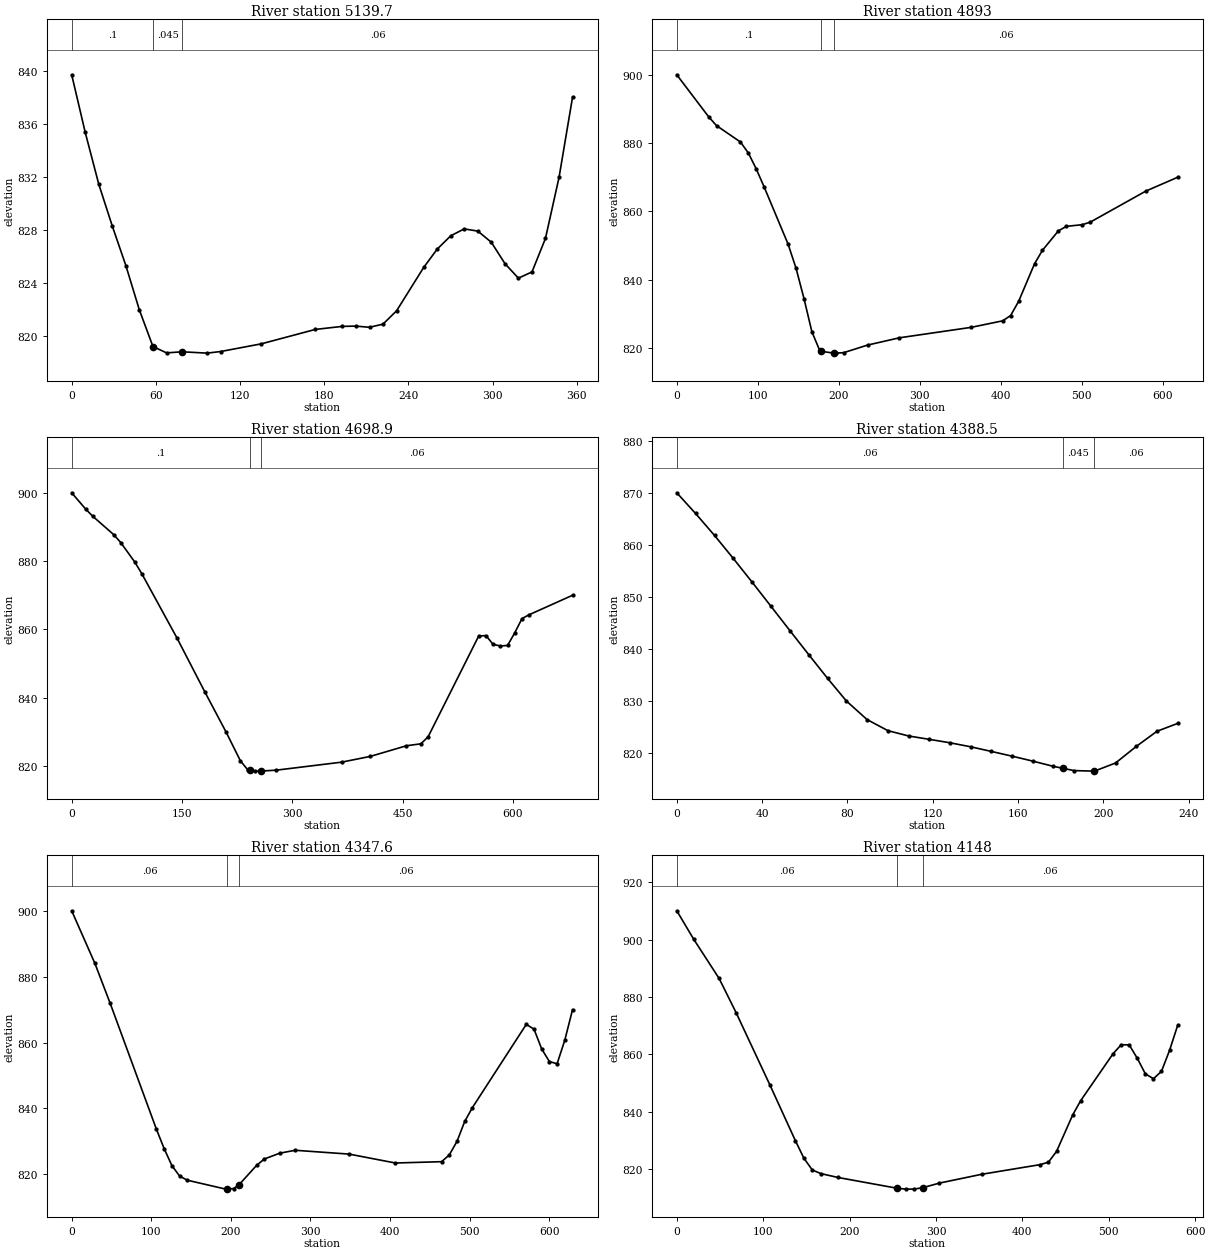
Type RM Length L Ch R = 1 ,5139.7  ,246.7,246.7,246.4
XS GIS Cut Line= 2
     1573349.389      285015.694     1573255.578      285360.178
#Sta/Elev= 30
       0  839.73     9.6   835.4    19.3  831.47      29  828.29    38.6  825.33
    48.2  821.99    57.9  819.22    67.6  818.74    78.8  818.82    96.5  818.72
   106.1  818.84   135.1  819.42   173.7  820.51     193  820.74   202.6  820.76
   212.3  820.67   221.9  820.91   231.6  821.92   250.9  825.19   260.5  826.57
   270.2  827.58   279.8   828.1   289.5  827.93   299.1  827.09   308.8  825.48
   318.4  824.38   328.1  824.85   337.7  827.38   347.4     832     357  838.04
#Mann= 3 , 0 , 0
       0      .1       0    57.9    .045       0    78.8     .06       0
Bank Sta=57.9,78.8
XS Rating Curve= 0 ,0
Exp/Cntr=0.3,0.1

Type RM Length L Ch R = 1 ,4893    ,195.7,194.1,192.5
XS GIS Cut Line= 2
     1573142.137      284859.643     1572990.243      285459.385
#Sta/Elev= 30
       0     900    39.3  887.72    49.1  885.12    78.6  880.33    88.4   877.1
    98.2  872.41     108   867.1   137.5   850.4   147.3  843.35   157.1  834.48
   166.9  824.73   176.8  819.13   178.6  819.02   193.6  818.51   196.4   818.5
   206.2  818.64   235.7  820.86     275  822.99   363.4  826.04   402.6  827.96
   412.4  829.51   422.3  833.68   441.9  844.66   451.7  848.62   471.4  854.31
   481.2  855.62   500.8  856.11   510.6  856.84   579.4  865.95   618.7     870
#Mann= 3 , 0 , 0
       0      .1       0   178.6    .045       0   193.6     .06       0
Bank Sta=178.6,193.6
XS Rating Curve= 0 ,0
Exp/Cntr=0.3,0.1

Type RM Length L Ch R = 1 ,4698.9  ,315.5,310.5,305.4
XS GIS Cut Line= 3
     1573054.559      284799.585     1572916.776      284957.755
     1572832.765      285421.538
#Sta/Elev= 30
       0     900    19.1  895.21    28.6  893.14    57.2  887.74    66.7  885.44
    85.8  879.72    95.4  876.29     143  857.55   181.2  841.64   209.8     830
   229.4  821.52   239.2  818.94   242.8  818.78     249   818.5   257.8  818.52
   278.5  818.79   366.9  821.12   406.2  822.82   455.2  825.93   474.9   826.5
   484.7  828.56   553.4  858.03   563.3  858.21   573.1  855.61   582.9  855.16
   592.7  855.29   602.5     859   612.4  863.18   622.2  864.31   681.1     870
#Mann= 3 , 0 , 0
       0      .1       0   242.8    .045       0   257.8     .06       0
Bank Sta=242.8,257.8
XS Rating Curve= 0 ,0
Exp/Cntr=0.3,0.1

Type RM Length L Ch R = 1 ,4388.5  ,53.5,40.8,28.1
XS GIS Cut Line= 3
     1572557.177      284791.525     1572596.547      284860.629
     1572603.542       285015.82
#Sta/Elev= 27
       0     870     8.8  866.03    17.7   861.8    26.5  857.38    35.4  852.79
    44.2  848.17      53  843.53    61.9  838.88    70.7  834.34    79.5     830
    89.2  826.42      99  824.28   108.7  823.26   118.4  822.61   128.1  821.95
   137.8  821.18   147.5  820.29   157.2  819.38   166.9  818.43   176.6  817.42
   180.9  817.06   186.3   816.6   195.9   816.5   205.8  818.07   215.5  821.25
   225.2  824.16   234.9  825.67
#Mann= 3 , 0 , 0
       0     .06       0   180.9    .045       0   195.9     .06       0
Bank Sta=180.9,195.9
XS Rating Curve= 0 ,0
Exp/Cntr=0.3,0.1

Type RM Length L Ch R = 1 ,4347.6  ,196,199.7,199.9
XS GIS Cut Line= 3
     1572446.808      284812.586      1572721.96      285210.924
     1572733.886      285355.567
#Sta/Elev= 30
       0  899.99      29  884.12    48.4  871.88   106.5  833.67   116.2  827.79
   125.9  822.67   135.6  819.48   145.2  818.24   193.6  815.53   195.2  815.56
   203.3  815.69   210.2  816.84   232.4  822.77   242.1  824.68   261.4  826.44
   280.8  827.32   348.6  826.16   406.7  823.46   464.8  823.86   474.4   825.9
   484.1  830.01   493.8  836.06   503.5  840.28   571.2  865.54   580.9  864.07
   590.6  858.04   600.2  854.25   609.9  853.58   619.6  860.76   629.3     870
#Mann= 3 , 0 , 0
       0     .06       0   195.2    .045       0   210.2     .06       0
Bank Sta=195.2,210.2
XS Rating Curve= 0 ,0
Exp/Cntr=0.3,0.1

Type RM Length L Ch R = 1 ,4148    ,246.8,248.9,253.4
XS GIS Cut Line= 3
     1572293.061      284893.429     1572525.655      285221.504
     1572609.053       285378.37
#Sta/Elev= 30
       0     910    19.6  900.08      49  886.42    68.7  874.48   107.9  849.24
   137.3  829.89   147.1   823.8   156.9  819.68   166.8  818.43   186.4  817.09
     255  813.33   264.8  813.02   274.6  813.03   284.7  813.52   304.1  815.13
   353.1   818.2   420.9  821.57   430.2  822.42   439.6  826.15   458.3  838.87
   467.6  843.87     505  860.19   514.4  863.32   523.7   863.3   533.1   858.6
   542.4   853.2   551.8  851.49   561.1  854.07   570.5  861.42   579.8  870.07
#Mann= 3 , 0 , 0
       0     .06       0     255    .045       0   284.7     .06       0
Bank Sta=255,284.7
XS Rating Curve= 0 ,0
Exp/Cntr=0.3,0.1

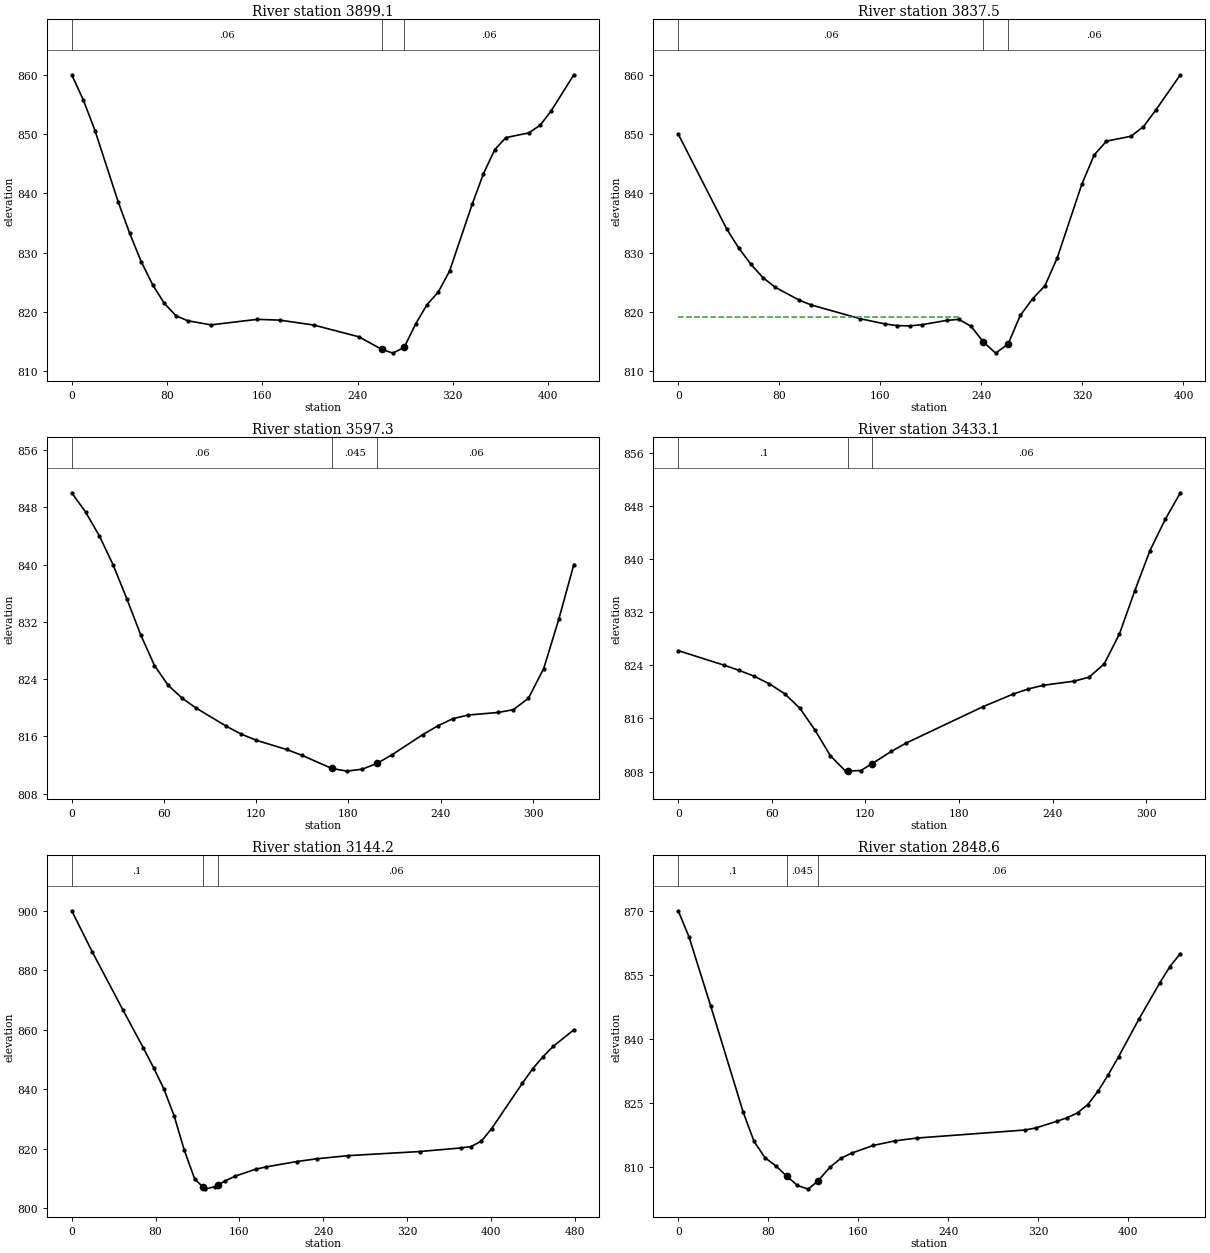
Type RM Length L Ch R = 1 ,3899.1  ,61.9,61.6,61.5
XS GIS Cut Line= 3
     1572153.639      285141.743     1572293.345      285210.437
     1572392.598      285457.187
#Sta/Elev= 30
       0     860     9.7  855.76    19.5   850.6    38.9   838.6    48.6  833.26
    58.4  828.42    68.1   824.5    77.8   821.4    87.6  819.32    97.3  818.49
   116.8  817.79   155.7  818.72   174.7  818.59   203.2  817.76   241.2  815.77
   260.2  813.67   269.7  813.02   279.2  814.02   288.7  817.92   298.2  821.18
   307.7  823.31   317.2  826.86   336.2  838.13   345.7  843.31   355.2  847.38
   364.6  849.41   383.6  850.19   393.2  851.47   402.6  853.93   421.6     860
#Mann= 3 , 0 , 0
       0     .06       0   260.2    .045       0   279.2     .06       0
Bank Sta=260.2,279.2
XS Rating Curve= 0 ,0
Exp/Cntr=0.3,0.1

Type RM Length L Ch R = 1 ,3837.5  ,237.6,240.1,242.1
XS GIS Cut Line= 3
     1572124.112       285171.78     1572234.326      285230.018
     1572338.755      285482.083
#Sta/Elev= 30
       0     850    38.4     834    47.9   830.8    57.5  828.07    67.1  825.81
    76.7   824.2    95.9     822   105.5  821.19   144.1  818.89   163.6  818.01
   173.4  817.73   183.1  817.68   192.9  817.88   212.4   818.6   222.1  818.78
   231.8  817.63   241.6  814.96   251.3  813.09   261.1   814.6   270.8  819.44
   280.6  822.26   290.3  824.44     300   829.1   319.5  841.54   329.3  846.48
     339  848.81   358.5  849.64   368.3  851.26     378  854.02   397.5  859.99
#Mann= 3 , 0 , 0
       0     .06       0   241.6    .045       0   261.1     .06       0
#XS Ineff= 2 , 0
          221.97  819.23
Permanent Ineff=
       F       F
Bank Sta=241.6,261.1
XS Rating Curve= 0 ,0
Exp/Cntr=0.3,0.1

Type RM Length L Ch R = 1 ,3597.3  ,155.4,164.2,173
XS GIS Cut Line= 3
      1572041.04       285194.21     1572056.039      285273.441
     1572065.057      285519.265
#Sta/Elev= 30
       0  850.01       9  847.32    17.9  844.02    26.9  839.95    35.8  835.22
    44.8  830.21    53.8   825.9    62.7  823.14    71.7  821.37    80.6     820
   100.3  817.46   110.2  816.33     120  815.47   139.7  814.18   149.5  813.39
   169.2  811.53     179  811.16   188.9  811.43   198.7  812.25   208.6  813.48
   228.2  816.24   238.1  817.48   247.9  818.48   257.8  818.99   277.4  819.35
   287.3  819.74   297.1  821.35     307  825.48   316.8  832.36   326.6     840
#Mann= 3 , 0 , 0
       0     .06       0   169.2    .045       0   198.7     .06       0
Bank Sta=169.2,198.7
XS Rating Curve= 0 ,0
Exp/Cntr=0.3,0.1

Type RM Length L Ch R = 1 ,3433.1  ,303.5,289,274
XS GIS Cut Line= 2
     1571930.202      285231.152     1571906.934      285552.224
#Sta/Elev= 27
       0  826.22    29.3  824.03      39  823.25    48.8  822.35    58.5  821.21
    68.3  819.71      78  817.53    87.8   814.2    97.6  810.36   107.3  808.06
   109.1  808.08   117.1  808.15   124.1  809.16   136.6  811.03   146.3  812.31
   195.1  817.74   214.6  819.66   224.4  820.44   234.1     821   253.6  821.61
   263.4  822.21   273.1  824.22   282.9  828.75   292.6  835.17   302.4  841.27
   312.2  845.99   321.9     850
#Mann= 3 , 0 , 0
       0      .1       0   109.1    .045       0   124.1     .06       0
Bank Sta=109.1,124.1
XS Rating Curve= 0 ,0
Exp/Cntr=0.3,0.1

Type RM Length L Ch R = 1 ,3144.2  ,313.2,295.6,277.3
XS GIS Cut Line= 3
     1571567.681      285252.341     1571763.321      285556.247
     1571868.209      285609.995
#Sta/Elev= 30
       0     900    19.5  886.24    48.8   866.7    68.4  853.87    78.2  847.19
    87.9  840.13    97.7  831.08   107.4  819.53   117.2  809.97     125  807.15
     127  806.43   136.8  807.27     140  807.91   146.5  809.22   156.3  810.84
   175.8  813.15   185.6  813.91   214.9  815.71   234.4  816.65   263.8  817.69
   332.1  819.07   371.2  820.27   381.1  820.74   390.9  822.53   400.7  826.72
   430.2  842.06     440   846.9   449.8  850.92   459.6  854.42   479.3     860
#Mann= 3 , 0 , 0
       0      .1       0     125    .045       0     140     .06       0
Bank Sta=125,140
XS Rating Curve= 0 ,0
Exp/Cntr=0.3,0.1

Type RM Length L Ch R = 1 ,2848.6  ,276.3,289.6,303.1
XS GIS Cut Line= 3
     1571419.944      285586.881     1571740.966      285652.001
     1571858.367      285633.854
#Sta/Elev= 30
       0     870     9.6  863.88    28.9  847.69    57.8  822.84    67.4  816.03
    77.1  812.22    86.7  810.32    96.3  807.93     106  805.71   115.6  804.86
     124  806.72   134.9  809.98   144.5  812.06   154.2  813.29   173.4  815.09
   192.7  816.16     212  816.81   308.3   818.7   317.9  819.18   336.7  820.74
   345.8  821.57     355  822.71   364.1  824.65   373.2  827.76   382.4  831.65
   391.5  835.85   409.8  844.76   428.1  853.11   437.2  856.96   446.4     860
#Mann= 3 , 0 , 0
       0      .1       0    96.3    .045       0     124     .06       0
Bank Sta=96.3,124
XS Rating Curve= 0 ,0
Exp/Cntr=0.3,0.1