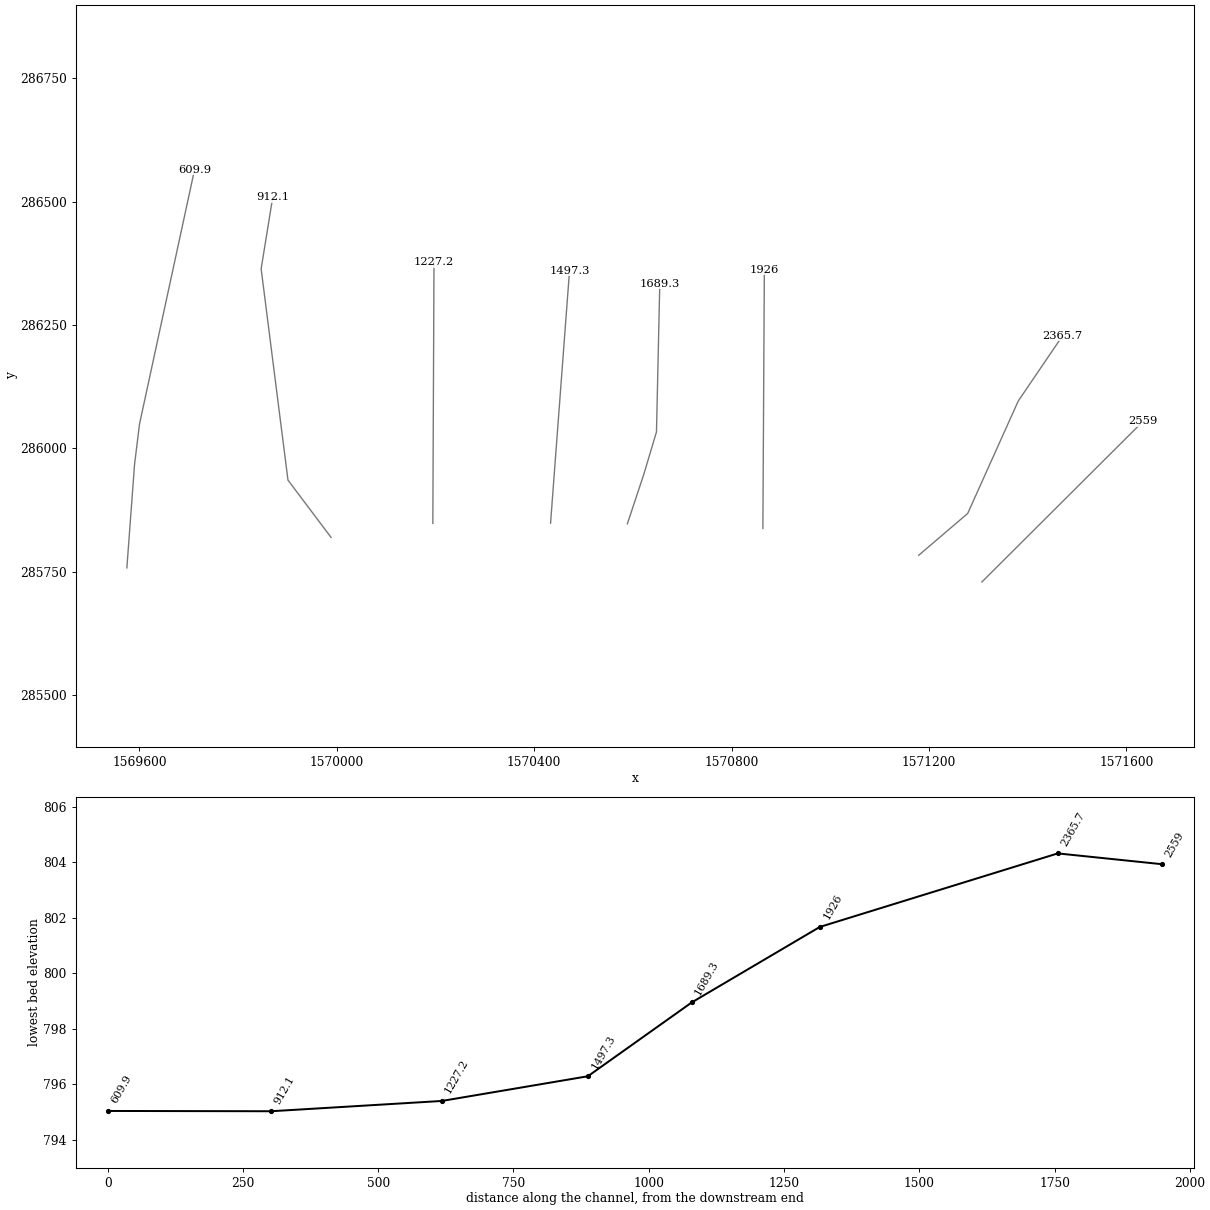
HEC-RAS study DOTSONRN.prj: DOTSONRN

--- DOTSONRN.g01 (geometry) --- (continued)

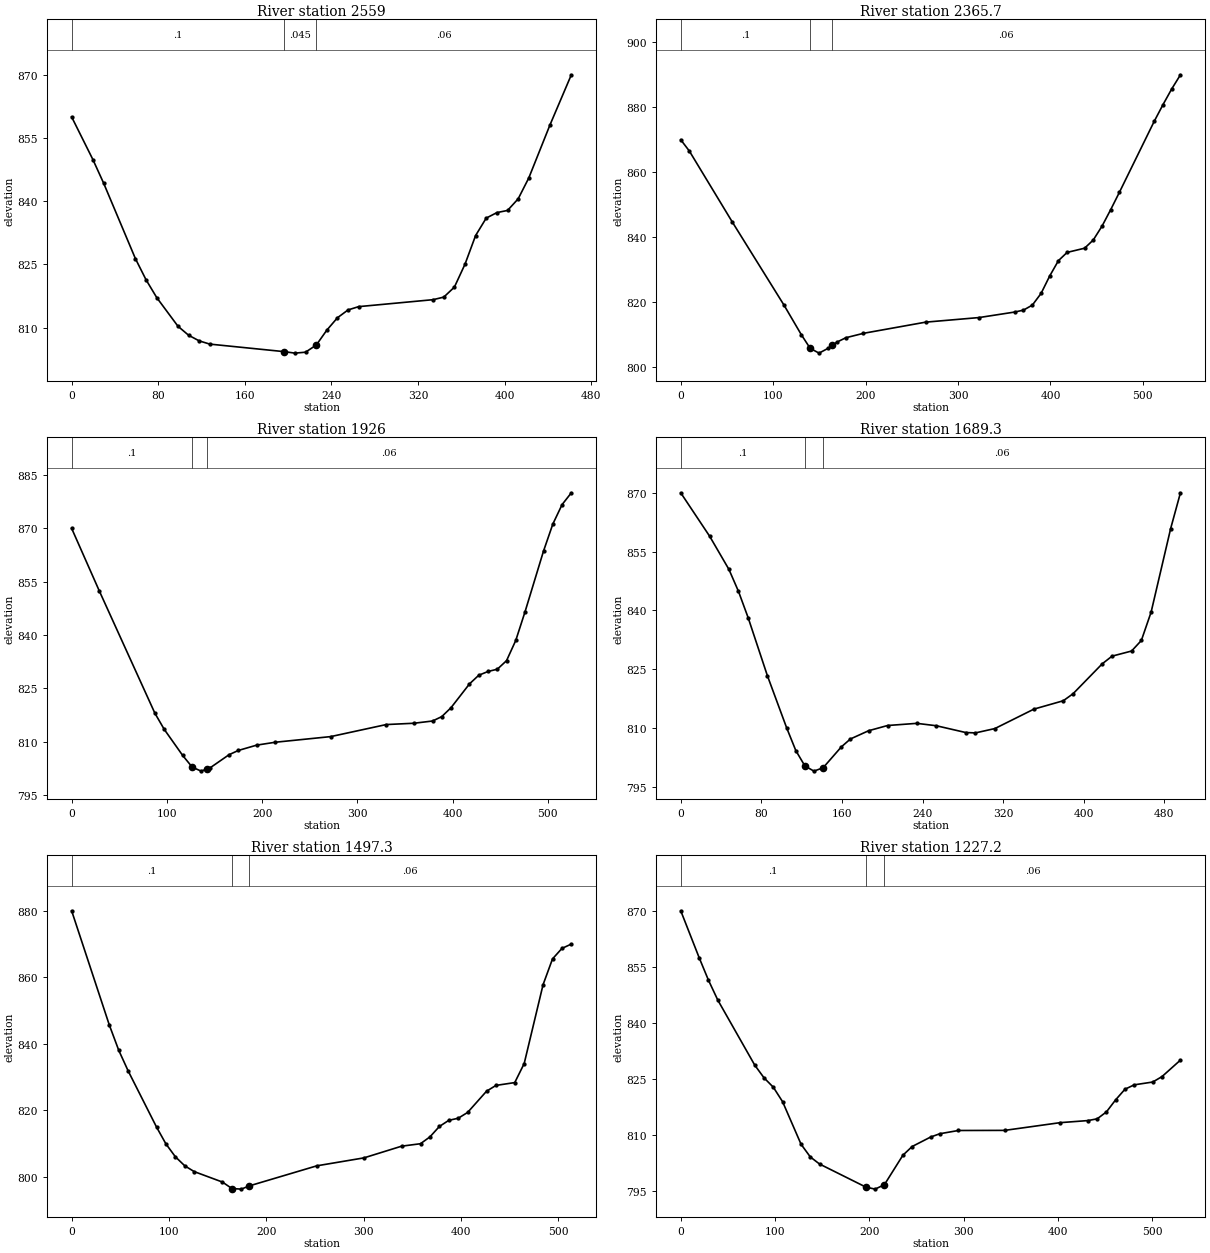
Type RM Length L Ch R = 1 ,2559    ,184.3,193.2,201.2
XS GIS Cut Line= 2
     1571307.193       285728.95     1571633.949      286054.832
#Sta/Elev= 30
       0     860    19.6  849.89    29.5   844.3    58.9  826.35    68.7  821.34
    78.6   817.1    98.2   810.3     108  808.17   117.8  806.83   127.6  806.06
   196.4  804.27   206.2  803.92     216  804.14     226  805.85   235.6  809.35
   245.5  812.32   255.3  814.18   265.1  814.96   333.8  816.61   343.7  817.22
   353.5  819.59   363.3  825.03   373.1  831.84   382.9  835.98   392.8  837.29
   402.6   837.8   412.4  840.55   422.2   845.5   441.8  858.11   461.5     870
#Mann= 3 , 0 , 0
       0      .1       0   196.4    .045       0     226     .06       0
Bank Sta=196.4,226
XS Rating Curve= 0 ,0
Exp/Cntr=0.3,0.1

Type RM Length L Ch R = 1 ,2365.7  ,429.6,439.8,448.8
XS GIS Cut Line= 4
     1571179.241      285783.147     1571278.413      285867.826
     1571380.862      286095.819     1571470.871      286228.352
#Sta/Elev= 30
       0     870     9.3  866.52    55.9  844.61   111.8  819.04   130.4     810
     140  805.79   149.6  804.31   159.2  805.76   163.7  806.66   168.9  807.69
   178.5  809.04   197.7  810.41     265  813.85   322.7  815.26   361.1  816.95
   370.7  817.54   380.4   819.1   389.8  822.68   399.2  828.08   408.6  832.78
     418  835.32   436.9  836.61   446.3  839.14   455.8  843.42   465.2  848.51
   474.6  853.84   512.3  875.71   521.7  880.79   531.1  885.61   540.6  889.99
#Mann= 3 , 0 , 0
       0      .1       0     140    .045       0   163.7     .06       0
Bank Sta=140,163.7
XS Rating Curve= 0 ,0
Exp/Cntr=0.3,0.1

Type RM Length L Ch R = 1 ,1926    ,243.1,236.7,230.2
XS GIS Cut Line= 2
     1570863.389      285837.403     1570866.329      286361.991
#Sta/Elev= 30
       0     870    29.1  852.35    87.4  817.96    97.2  813.42   116.6  806.06
   126.6  802.78     136  801.66   141.6  802.23   145.7  802.65   165.2  806.27
   174.9  807.47   194.3  808.98   213.7  809.79     272  811.38   330.3  814.77
   359.4  815.14   378.9  815.77   388.6  817.01   398.3  819.52   417.7  826.22
   427.4  828.65   437.2  829.72   446.9  830.35   456.6  832.76   466.3  838.47
     476  846.51   495.4   863.6   505.2  871.22   514.9  876.69   524.6  880.01
#Mann= 3 , 0 , 0
       0      .1       0   126.6    .045       0   141.6     .06       0
Bank Sta=126.6,141.6
XS Rating Curve= 0 ,0
Exp/Cntr=0.3,0.1

Type RM Length L Ch R = 1 ,1689.3  ,187,192,196.7
XS GIS Cut Line= 4
     1570588.697       285846.82     1570621.869      285946.565
     1570647.752      286033.238     1570654.459      286333.554
#Sta/Elev= 30
       0     870    28.7  858.91    47.8  850.46    57.3  844.84    66.9  838.11
      86   823.3   105.1     810   114.2  804.19   123.2  800.27   132.2  798.94
   141.3   799.8   159.4  805.13   168.4  807.15   186.5  809.26   205.3  810.59
   234.3  811.14   253.7  810.53   282.8   808.8   292.5   808.7   311.8  809.81
   350.6  814.78   379.7  816.91   389.4   818.7   418.4  826.35   428.1   828.3
   447.5  829.61   457.2   832.3   466.9  839.55   486.3  860.89     496  870.01
#Mann= 3 , 0 , 0
       0      .1       0   123.2    .045       0   141.3     .06       0
Bank Sta=123.2,141.3
XS Rating Curve= 0 ,0
Exp/Cntr=0.3,0.1

Type RM Length L Ch R = 1 ,1497.3  ,268.3,270,271.1
XS GIS Cut Line= 2
     1570433.113      285848.141     1570471.543      286359.946
#Sta/Elev= 30
       0     880    38.7  845.64    48.4  838.02    58.1   831.8    87.2  814.94
    96.8   809.9   106.5  806.02   116.2  803.29   125.9  801.55   154.9   798.4
   164.6  796.46   174.3  796.28   182.3  797.24   251.8  803.29   300.2  805.68
   338.9   809.2   358.3  809.94     368     812   377.7  815.13   387.4  816.98
     397   817.6   406.7  819.35   426.1  825.73   435.8  827.48   455.1  828.33
   464.8  834.06   484.2  857.79   493.9  865.54   503.6   868.7   513.2     870
#Mann= 3 , 0 , 0
       0      .1       0   164.6    .045       0   182.3     .06       0
Bank Sta=164.6,182.3
XS Rating Curve= 0 ,0
Exp/Cntr=0.3,0.1

Type RM Length L Ch R = 1 ,1227.2  ,312.2,315.2,317.9
XS GIS Cut Line= 2
     1570194.547      285847.687     1570196.902      286377.731
#Sta/Elev= 30
       0     870    19.6  857.38    29.4  851.39    39.3  846.06    78.5  828.62
    88.3  825.23    98.2   822.7     108  818.83   127.6  807.42   137.4  804.02
   147.2  802.12   196.3  795.94   206.1  795.39     216  796.58   235.6  804.47
   245.4  806.81     265  809.35   274.8  810.24   294.5  811.11   343.6  811.14
   402.4  813.21   431.9  813.77   441.7  814.24   451.5  816.09   461.3  819.34
   471.2  822.18     481  823.35   500.6   824.1   510.4  825.55     530  829.98
#Mann= 3 , 0 , 0
       0      .1       0   196.3    .045       0     216     .06       0
Bank Sta=196.3,216
XS Rating Curve= 0 ,0
Exp/Cntr=0.3,0.1

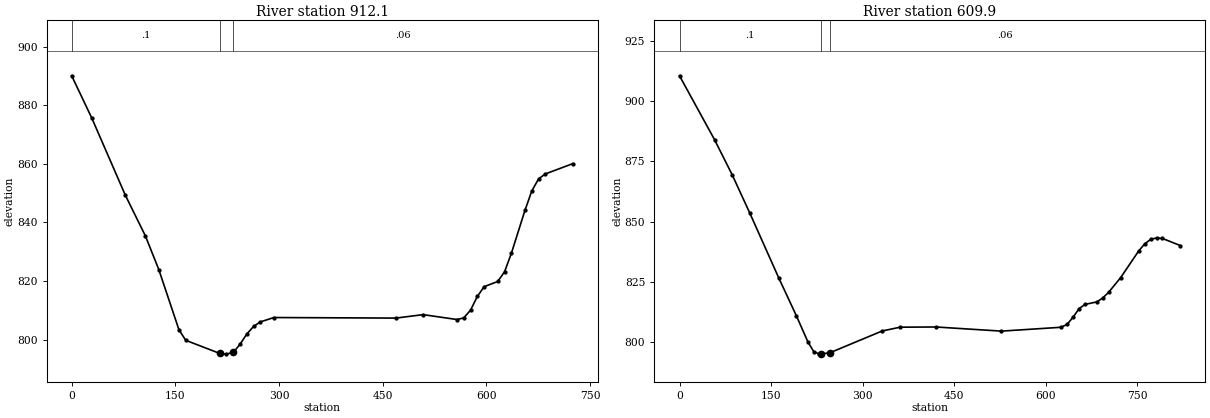
Type RM Length L Ch R = 1 ,912.1   ,307.6,302.2,296.7
XS GIS Cut Line= 4
     1569988.311      285819.289     1569900.973      285935.479
     1569846.617      286363.847     1569870.202       286509.54
#Sta/Elev= 30
       0     890    29.1  875.56    77.5  849.32   106.6  835.38     126   823.9
   155.2  803.34     165  799.74     214  795.28   223.9  795.02   234.1  795.68
   243.5  798.34   253.3  801.85   263.1  804.45   272.9  806.01   292.6  807.51
   469.2  807.32   508.5   808.5   557.5  806.83   567.3  807.38   577.2  810.03
     587  814.72   596.8  818.03   616.5  819.81   626.4  823.13   636.2  829.38
   655.9  844.08   665.7  850.64   675.6  854.83   685.4  856.52   724.8     860
#Mann= 3 , 0 , 0
       0      .1       0     214    .045       0   234.1     .06       0
Bank Sta=214,234.1
XS Rating Curve= 0 ,0
Exp/Cntr=0.3,0.1

Type RM Length L Ch R = 1 ,609.9   ,601.7,609.9,618
XS GIS Cut Line= 4
     1569574.485      285757.449      1569590.11      285967.518
     1569600.129      286049.164     1569711.638       286564.74
#Sta/Elev= 30
       0  910.56    57.4  884.04    86.2   869.5   114.9  853.71   162.8  826.52
   191.5   810.9   210.6  799.94   219.8  796.12   228.9  795.03   231.7  795.06
   246.7  795.64     332  804.64   361.3  806.21   419.9   806.3   527.4  804.58
     625  806.18   634.8  807.36   644.6  810.34   654.3  813.86   664.1  815.67
   683.6  816.71   693.4  818.36   703.2   820.8   722.7  826.83     752  837.82
   761.8  840.74   771.6  842.64   781.3  843.28   791.1  843.04   820.4  840.09
#Mann= 3 , 0 , 0
       0      .1       0   231.7    .045       0   246.7     .06       0
Bank Sta=231.7,246.7
XS Rating Curve= 0 ,0
Exp/Cntr=0.3,0.1

Chan Stop Cuts=-1
Use User Specified Reach Order=0
Composite Channel Slope=5